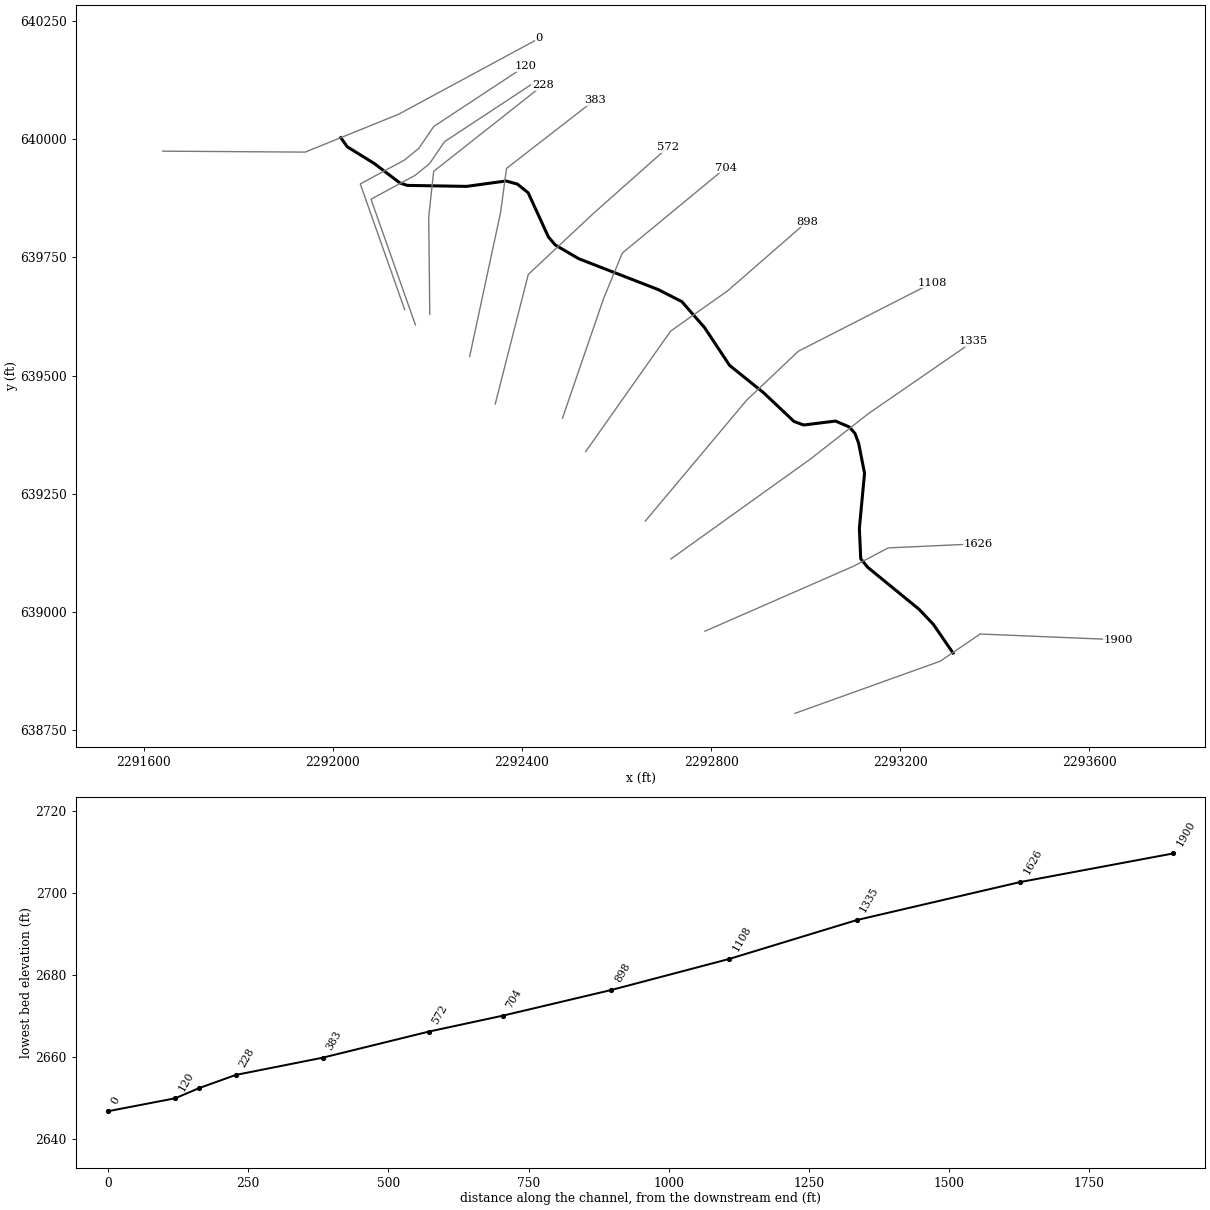
--- RFFILSCKT1.prj (project) ---

Proj Title=RFFILSCKT1
Current Plan=p01
Default Exp/Contr=0,0
English Units
Geom File=g01
Flow File=f01
Plan File=p01
BEGIN DESCRIPTION:
----------MODEL BY WOOD PLC 2022----------
AFH study
Randolph County, WV
HEC-RAS Version: RAS 6.2
Vertical Datum: NAVD88
Projection: NAD 1983 StatePlane West Virginia S FIPS 4702 (US Feet)
Terrain: 1-meter LIDAR (FEMA Region III 3DEP collected 2016-2018)
Land Use: 2019 NLCD
Hydrologic Method:
WV SIR2010-5033 regression equations
Additional Model Notes:
Shared XS with RFFILESCK due to name change
END DESCRIPTION:
DSS Export Rating Curves= 0
DSS Export Rating Curve Sorted= 0
DSS Export Volume Flow Curves= 0
DXF OffsetX= 0
DXF OffsetY= 0
DXF ScaleX= 0
DXF ScaleY= 0

--- RFFILSCKT1.p01 (plan) ---

Plan Title=Floodplain
Program Version=6.20
Short Identifier=Floodplain
Geom File=g01
Flow File=f01
Subcritical Flow
K Sum by GR= 0
Std Step Tol= 0.01
Critical Tol= 0.01
Num of Std Step Trials= 20
Max Error Tol= 0.3
Flow Tol Ratio= 0.001
Split Flow NTrial= 30
Split Flow Tol= 0.02
Split Flow Ratio= 0.02
Log Output Level= 0
Friction Slope Method= 1
Unsteady Friction Slope Method= 2
Unsteady Bridges Friction Slope Method= 1
Parabolic Critical Depth
Global Vel Dist= 0 , 0 , 0
Global Log Level= 0
CheckData=True
Encroach Param=-1 ,0,0, 0
Mapping Interval=1HOUR
Computation Time Step Use Courant=        0
Computation Time Step Use Time Series=    0
Computation Time Step Count To Double=0
Computation Time Step Max Doubling=0
Computation Time Step Max Halving=0
Computation Time Step Residence Courant=0
Run HTab= 0
Run UNet= 0
Run Sediment= 0
Run PostProcess= 0
Run WQNet= 0
Run RASMapper=-1
UNET Theta= 0
UNET Theta Warmup= 0
UNET ZTol= 0
UNET ZSATol= 0
UNET MxIter= 0
UNET Max Iter WO Improvement= 0
UNET MaxInSteps= 0
UNET DtIC= 0
UNET DtMin= 0
UNET MaxCRTS= 0
UNET WFStab= 0
UNET SFStab= 0
UNET WFX= 1
UNET SFX= 1
UNET Gravity=32.174
UNET 1D Methodology=Finite Difference
UNET DSS MLevel= 1
UNET Pardiso=0
UNET DZMax Abort= 0
UNET Use Existing IB Tables= 0
UNET Froude Reduction=False
UNET Froude Limit= 0
UNET Froude Power= 0
UNET D1 Cores= 0
UNET WindReference=Eulerian
UNET WindDragFormulation=Hsu (1988)
UNET D2 Coriolis=0
UNET D2 Cores= 0
UNET D2 Theta= 1
UNET D2 Theta Warmup= 1
UNET D2 Z Tol= 0.01
UNET D2 Volume Tol= 0.01
UNET D2 Max Iterations= 20
UNET D2 Equation= 0
UNET D2 RampUpFraction=0.1
UNET D2 TimeSlices= 1
UNET D2 Turbulence Formulation=Non-Conservative (original)
UNET D2 Eddy Viscosity=0.3
UNET D2 Transverse Eddy Viscosity=0.1
UNET D2 Smagorinsky Mixing=0
UNET D2 BCVolumeCheck=0
UNET D2 Cores=0
UNET D2 SolverType=PARDISO (Direct)
UNET D2 Minimum Iterations= 2147483647
UNET D2 Maximum Iterations= 2147483647
UNET D2 Restart Number= 10
UNET D2 Relaxation Coeff=1.3
UNET D2 SOR Precondition Iterations= 10
UNET D2 ILUT Maximum Fill= 8
UNET D2 ILUT Tolerance=1E-08
UNET D1D2 MaxIter= 0
UNET D1D2 ZTol=0.01
UNET D1D2 QTol=0.1
UNET D1D2 MinQTol=1
Write IC File= 0
Write IC File at Fixed DateTime=0
Write IC File at Sim End=0
Echo Input=False
Echo Parameters=False
Echo Output=False
Write Detailed= 0
HDF Write Warmup=0
HDF Write Time Slices=0
HDF Flush=0
HDF Compression= 1
HDF Chunk Size= 1
HDF Spatial Parts= 1
HDF Use Max Rows=0
HDF Fixed Rows= 1
Calibration Method= 0
Calibration Iterations= 20
Calibration Max Change=0.05
Calibration Tolerance=0.2
Calibration Maximum=1.5
Calibration Minimum=0.5
Calibration Optimization Method= 1
WQ AD Non Conservative
WQ ULTIMATE=-1
WQ Max Comp Step=1HOUR
WQ Output Interval=15MIN
WQ Output Selected Increments= 0
WQ Output face flow=0
WQ Output face velocity=0
WQ Output face area=0
WQ Output face dispersion=0
WQ Output cell volume=0
WQ Output cell surface area=0
WQ Output cell continuity=0
WQ Output cumulative cell continuity=0
WQ Output face conc=0
WQ Output face dconc_dx=0
WQ Output face courant=0
WQ Output face peclet=0
WQ Output face adv mass=0
WQ Output face disp mass=0
WQ Output cell mass=0
WQ Output cell source sink temp=0
WQ Output nsm pathways=0
WQ Output nsm derived pathways=0
WQ Create Restart=0
WQ Fixed Restart=0
WQ System Summary=0
WQ Write To DSS=0
Sorting and Armoring Iterations= 10
XS Update Threshold= 0.02
Bed Roughness Predictor= 0
Hydraulics Update Threshold= 0.02
Energy Slope Method= 1
Volume Change Method= 1
Sediment Retention Method= 0
Sediment TS Multiplier= 1
Warm Up Method= 0
XS Weighting Method= 0
Number of US Weighted Cross Sections= 1
Number of DS Weighted Cross Sections= 1
Upstream XS Weight=0
Main XS Weight=1
Downstream XS Weight=0
Number of DS XS's Weighted with US Boundary= 1
Upstream Boundary Weight= 1
Weight of XSs Associated with US Boundary= 0
Number of US XS's Weighted with DS Boundary= 1
Downstream Boundary Weight= 0.5
Weight of XSs Associated with DS Boundary= 0.5
Percentile Method= 0
Sediment Output Level= 3
Mass or Volume Output= 0
Output Increment Type= 1
Profile and TS Output Increment= 1
Transport Output Increment 1
XS Output Flag= 0
XS Output Increment= 10
Read HDF5 Sediment Hotstart= 0
Sediment Hotstart Type= 0
Write Gradation File= 0
Read Gradation Hotstart= 0
Write HDF5 File= 1
Write Binary Output= 1
Write DSS Sediment File= 0
DSS Sediment Output Type= 1
SV Curve= 0
Specific Gage Flag= 0
Subcell Erosion Methods= 0
Subcell Deposition Methods= 0
Advection Scheme= 1
Matrix Solver= 0
Implicit Weighting Factor= 1
Maximum Outer Loop Convergence Iterations= 5
Convergence Maximum Absolute= 0.001
Convergence RMSE= 0.0001
Grain Fractions Max Abs Error= 0.001
Max Subgrid Regions= 1
Max Subgrid Length Scale= 3.402823E+38
Initial Layer Thickness= 3.402823E+38
Min Layer Thickness= 3.402823E+38
Max Layer Thickness= 3.402823E+38
Number of Layers= 5

--- RFFILSCKT1.f01 (steady flow) ---

Flow Title=Flow
Program Version=6.20
Number of Profiles= 1
Profile Names=P100yr
River Rch & RM=RFFILSCKT1,Main            ,1900
     572
River Rch & RM=RFFILSCKT1,Main            ,0
     640
Boundary for River Rch & Prof#=RFFILSCKT1,Main            , 1
Up Type= 0
Dn Type= 1
Dn Known WS=2649.8
DSS Import GetInterval= 0
DSS Import GetPeak= 0
DSS Import FillOption= 0

--- RFFILSCKT1.g01 (geometry) ---

Geom Title=Geometry
Program Version=6.20

River Reach=RFFILSCKT1      ,Main
Reach XY= 30
2293311.79482768638913.2055855842293269.84500003638974.210999995
2293239.63700001639005.981999993     2293131.303639094.524000019
     2293116.487639112.5550000072293113.59500003      639176.816
2293124.53200004639293.4820000082293112.03200004639357.024000004
2293104.22000001639377.857000008     2293092.241639391.399000019
2293063.07400002639403.8990000192292995.97600003639395.540000021
2292975.57399999639402.856999993     2292910.991639463.795000002
     2292839.116639521.6069999932292785.99099998639601.814999998
2292738.07400002639656.5030000062292688.07400003639682.024000004
     2292520.366639747.1280000062292470.36600001639776.295000002
2292455.78200004639793.4820000082292413.07400002639886.710999995
     2292390.388639904.990999997     2292366.199 639911.71100001
2292282.86600003639900.2530000062292157.34500003 639902.33600001
2292141.72000001639907.5450000172292087.55300003639948.691000015
2292030.50413501639983.9604880362292016.62687413640003.246264777

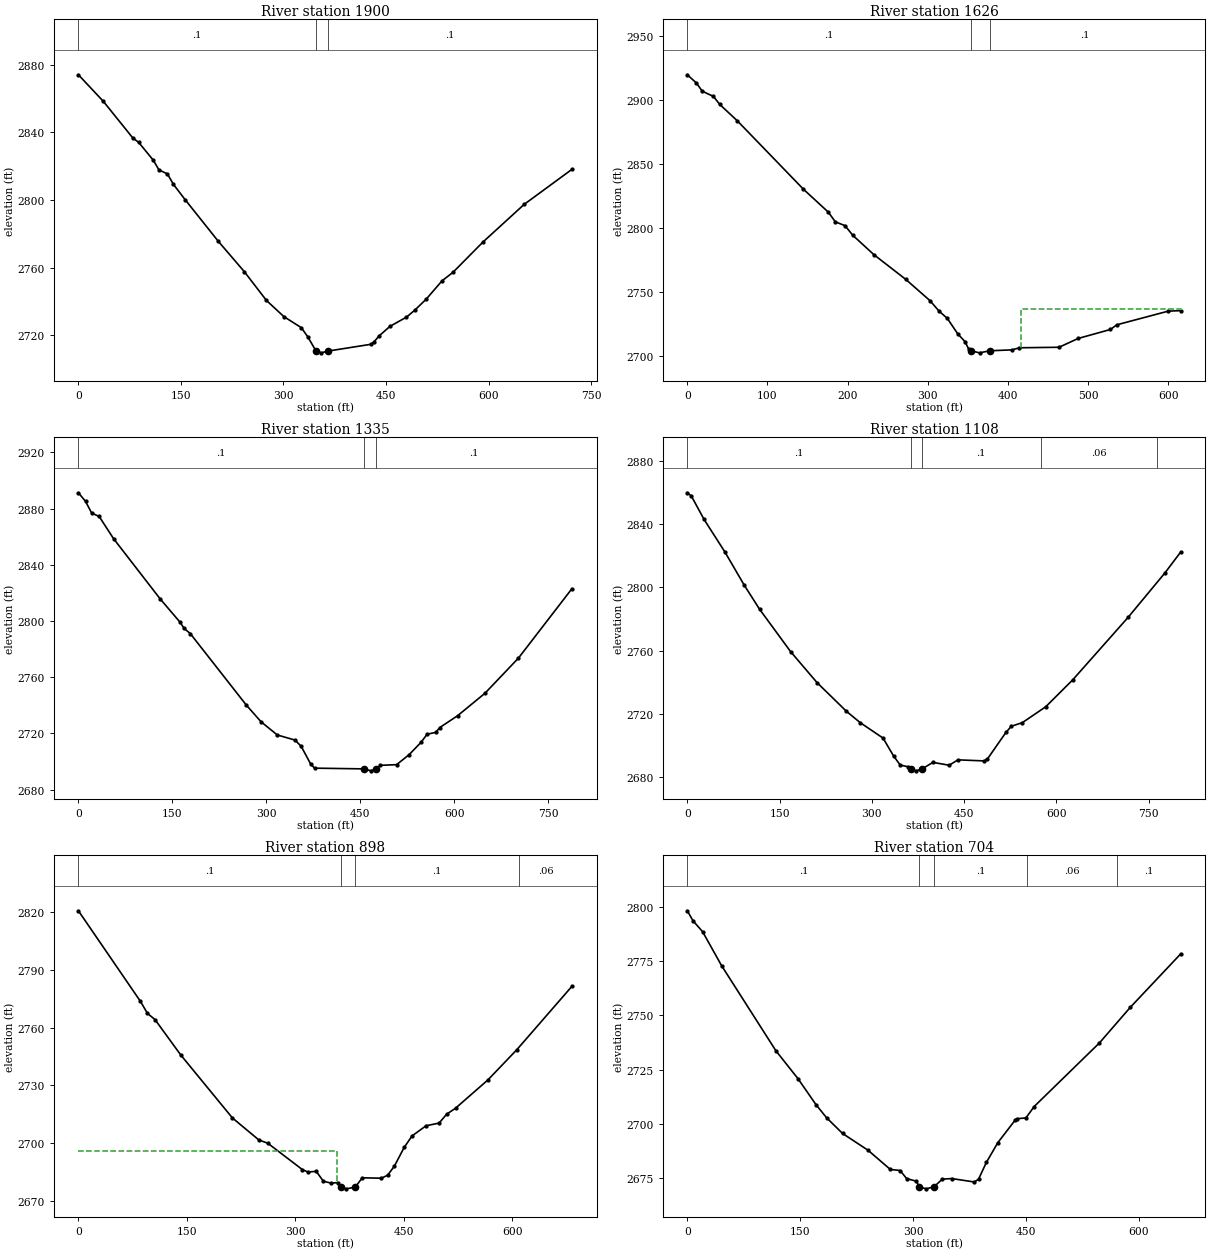
Type RM Length L Ch R = 1 ,1900    ,274.7,273.7,271
XS GIS Cut Line= 4
 2292977.2286451638785.606341676 2293284.6640143638896.004283878
2293369.02426177638953.4661507082293661.93047308638941.268909705
#Sta/Elev= 30
       0 2874.06    36.4 2858.37    79.6 2836.68    88.1  2834.1   109.4  2823.6
   117.9 2817.77   130.2 2815.42   139.1 2809.18   156.1  2800.2   204.5 2775.62
   242.8 2757.54   275.1 2740.55   300.6 2730.99   326.1 2724.45   335.5 2719.08
  347.592710.648   355.1 2709.55  365.882710.648   427.7 2714.59   431.9 2715.73
   439.7  2719.5   455.9 2725.24   479.9 2730.66   491.9 2734.72   508.9 2741.34
     532 2752.16     548 2757.19     592 2775.16   652.1 2797.37   721.9 2818.07
#Mann= 3 ,-1,0
       0      .1       0  347.59    .045       0  365.88      .1       0
Bank Sta=347.59,365.88
XS Rating Curve= 0 ,0
Exp/Cntr=0.3,0.1

Type RM Length L Ch R = 1 ,1626    ,287.1,291.3,288.1
XS GIS Cut Line= 4
 2292787.0318764638959.4465715062293100.28316501639096.431815008
2293174.53091334639135.5683306772293363.80619864639144.306537484
#Sta/Elev= 30
       0 2919.73    11.3 2913.37    18.7 2906.88    32.6 2902.84    40.5 2896.56
    62.4 2883.76   144.9  2830.3   175.9 2812.42   184.6 2804.85   196.6 2801.92
   206.4 2794.35   232.6 2779.28   272.5 2759.89   302.5 2743.39   313.8 2735.24
   324.2 2729.48   337.4 2717.25   346.3 2711.33   350.8 2705.56   353.22704.212
   364.4 2702.56   377.22704.171   405.1 2704.89   414.1 2706.52   463.5 2706.91
   487.5 2713.82   527.6  2720.8   535.6 2724.46   599.7 2735.13   615.3 2735.52
#Mann= 3 ,-1,0
       0      .1       0   353.2    .045       0   377.2      .1       0
#XS Ineff= 2 , 0
                          416.33            2737
Permanent Ineff=
       F       F
Bank Sta=353.2,377.2
XS Rating Curve= 0 ,0
Exp/Cntr(USF)=0,0
Exp/Cntr=0.3,0.1

Type RM Length L Ch R = 1 ,1335    ,221.3,226.9,223.5
XS GIS Cut Line= 4
2292714.92748101639112.169019228 2293011.1343328639324.351631155
2293133.17128141639419.9652580022293354.38467073 639572.43778454
#Sta/Elev= 30
       0 2891.26    11.4 2885.15    21.2 2876.82    33.2 2874.38    56.1 2858.63
   130.6  2815.7   162.2  2799.2   168.8 2794.72   178.7 2791.01   268.2  2740.1
   291.8  2728.2   317.7 2718.83     346 2715.19   355.8 2710.75   370.8  2698.3
   377.1 2695.21   456.42694.691   467.3  2693.3  474.762694.693   482.4 2697.22
   508.2 2697.69   528.2 2704.81   547.3 2713.63   556.9 2719.36   570.9 2720.71
   577.1 2724.11   605.6 2732.53   649.4 2748.56   702.8 2773.56   788.1 2822.91
#Mann= 3 ,-1,0
       0      .1       0   456.4    .045       0  474.76      .1       0
Bank Sta=456.4,474.76
XS Rating Curve= 0 ,0
Exp/Cntr=0.3,0.1

Type RM Length L Ch R = 1 ,1108    ,211.4,210.4,208.8
XS GIS Cut Line= 4
2292660.71439469639192.2752052672292875.30959238639448.166205805
2292984.58407856 639551.653415952293267.69207927639696.137830896
#Sta/Elev= 30
       0 2859.84     6.4 2857.91    27.3 2842.96    61.4 2822.22    92.5 2801.41
   117.4  2786.2   168.2 2759.19   210.8 2739.76   258.6 2721.58   281.3 2714.31
   318.3 2704.57   335.3 2693.31   346.2  2687.5   358.7 2686.45  364.092684.893
   372.1 2683.85  380.992684.894   399.4 2689.21   425.8 2687.39   440.1  2690.8
   482.4 2690.14   487.8 2691.26     518 2708.13   526.9 2712.08   544.8 2714.36
   582.8 2724.41   626.8 2741.49   716.6 2780.94   776.7 2809.17   802.3 2822.39
#Mann= 5 ,-1,0
       0      .1       0  364.09    .045       0  380.99      .1       0
  574.46     .06       0  764.46      .1       0
Bank Sta=364.09,380.99
XS Rating Curve= 0 ,0
Exp/Cntr(USF)=0,0
Exp/Cntr=0.3,0.1

Type RM Length L Ch R = 1 ,898     ,187.9,193.7,198.7
XS GIS Cut Line= 4
2292534.63874111639339.2021335352292714.43329731639594.179148306
2292834.79179479639679.2274468982293002.75666768639825.449472493
#Sta/Elev= 30
       0 2820.66    85.8  2773.6    95.4  2767.4   105.9 2764.16   141.5 2745.78
   212.9 2713.09   249.4 2701.67   261.8 2699.96   309.7 2686.25   317.2 2685.02
   328.8 2685.36   338.6 2680.23   349.8  2679.2   358.2 2679.55  363.482677.114
   369.9 2676.28  382.462677.113   392.5 2682.01   418.7  2681.8   427.3  2683.3
   436.6 2687.94   450.3 2697.78   461.2 2703.75   480.6 2709.04   498.6 2710.42
   508.9    2715   521.3 2718.14   565.9 2732.77   606.3 2748.63   682.1 2781.39
#Mann= 4 ,-1,0
       0      .1       0  363.48    .045       0  382.46      .1       0
  609.37     .06       0
#XS Ineff= 2 , 0
          357.66 2696.07
Permanent Ineff=
       F       F
Bank Sta=363.48,382.46
XS Rating Curve= 0 ,0
Exp/Cntr(USF)=0,0
Exp/Cntr=0.3,0.1

Type RM Length L Ch R = 1 ,704     ,136.8,131.9,128.8
XS GIS Cut Line= 4
2292485.62515048 639409.992505062292572.66627268639663.203042352
2292612.23041913 639759.287398022292831.52883089639940.152067514
#Sta/Elev= 30
       0 2798.29     7.6 2793.67    20.3 2788.67    45.7 2772.91   117.8  2733.7
   147.2 2720.81   171.3 2708.75   185.2 2702.79   206.4 2695.56   240.2 2687.83
   269.9 2678.96   282.9 2678.48   291.5 2674.77   304.5 2673.53  308.472670.949
   317.5 2670.02  327.832670.947   339.1 2674.51   351.6 2674.76   381.5 2673.18
   387.1 2674.46   397.5 2682.18   412.7 2691.29   435.5 2701.59   438.3 2702.38
   450.1 2702.73   461.1    2708   547.9 2737.36   588.9 2753.77   655.9 2778.43
#Mann= 5 ,-1,0
       0      .1       0  308.47    .045       0  327.83      .1       0
  451.66     .06       0  571.66      .1       0
Bank Sta=308.47,327.83
XS Rating Curve= 0 ,0
Exp/Cntr(USF)=0,0
Exp/Cntr=0.3,0.1

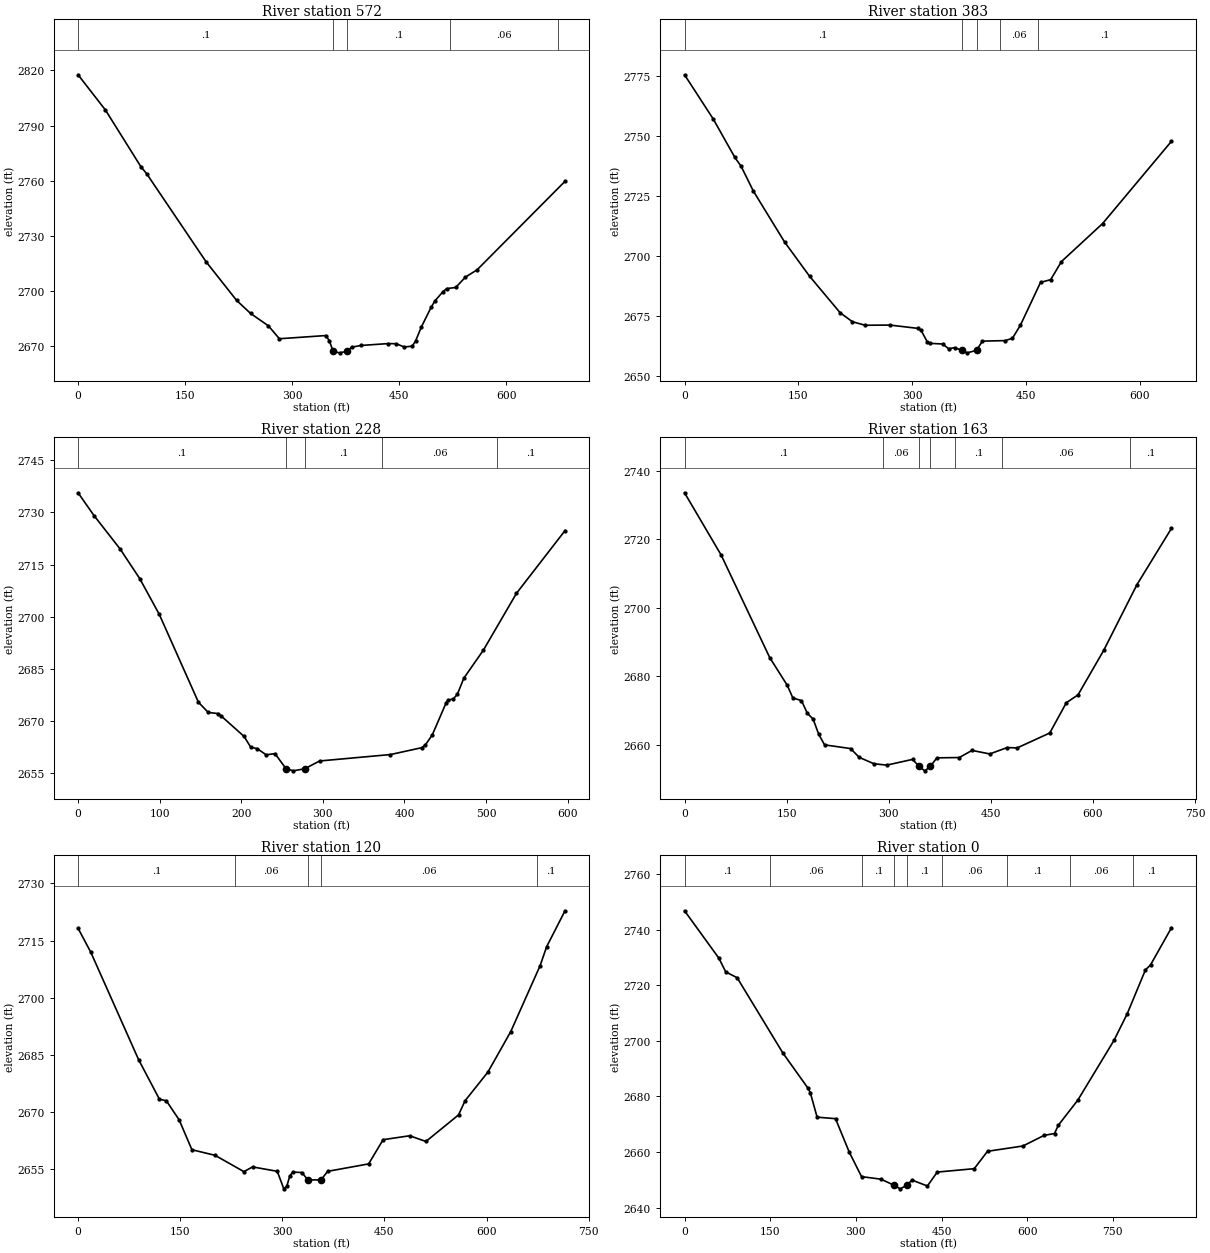
Type RM Length L Ch R = 1 ,572     ,178.8,189,192.4
XS GIS Cut Line= 4
2292343.40098233 639439.970010152292413.30642868639714.024268308
2292551.12636816639843.0715346612292708.48992368639982.794698809
#Sta/Elev= 30
       0 2817.66    38.4 2798.41    87.9 2767.63    96.2 2763.67   179.2 2715.83
     222 2694.75   241.7 2687.58   266.6 2680.86     282 2673.82     347 2675.56
   351.8 2672.86  357.332666.907   366.3 2666.14  376.222666.905   383.3 2669.23
   396.4 2670.16   434.2 2671.18   445.6 2671.09   456.9 2669.33   468.2  2669.8
     473  2672.8   480.8 2680.18   494.4 2690.85   499.8 2694.42     511 2699.42
   516.4 2701.15     529 2701.75   542.6 2707.41   558.9 2711.36   682.1 2759.61
#Mann= 5 ,-1,0
       0      .1       0  357.33    .045       0  376.22      .1       0
  521.64     .06       0  671.64      .1       0
Bank Sta=357.33,376.22
XS Rating Curve= 0 ,0
Exp/Cntr(USF)=0,0
Exp/Cntr=0.3,0.1

Type RM Length L Ch R = 1 ,383     ,155.1,155,155
XS GIS Cut Line= 4
 2292289.2476276639540.351462362 2292354.8110703639845.560592133
2292367.24551632639938.2537352492292553.76220674640082.945470844
#Sta/Elev= 30
       0 2775.68    37.7 2757.31    66.3 2741.24    74.5 2737.58    90.7  2727.2
   131.8 2706.01   164.8 2691.71   205.2 2676.46   221.3 2672.75   238.1 2671.29
   270.9 2671.36   307.7 2669.98   311.8 2669.13   319.9  2664.4   323.7 2663.75
     340 2663.47   348.1 2661.53   356.2 2661.96  365.632660.807   372.3 2659.79
  384.872660.809   392.5 2664.67   422.7 2664.89   432.2 2665.87   442.7 2671.32
   469.2 2689.14   482.6  2690.3   496.8 2697.84     551 2713.67   641.8 2747.97
#Mann= 5 ,-1,0
       0      .1       0  365.63    .045       0  384.87      .1       0
   415.7     .06       0   465.7      .1       0
Bank Sta=365.63,384.87
XS Rating Curve= 0 ,0
Exp/Cntr(USF)=0,0
Exp/Cntr=0.3,0.1

Type RM Length L Ch R = 1 ,228     ,73.9,64.8,60.1
XS GIS Cut Line= 4
2292204.98267735639629.6857803542292202.65210982639834.687597084
2292213.12470925639931.9586618452292443.75534258640113.984806678
#Sta/Elev= 30
       0 2735.66    19.5 2729.11    51.5 2719.48    75.5 2710.97    99.5 2700.65
   147.5 2675.34   159.5 2672.41   171.5 2672.08   175.5 2671.36   203.5 2665.48
   211.5 2662.42   219.6 2661.97   230.5  2660.2   241.3 2660.55  254.81 2656.21
   263.8 2655.59   277.7 2656.19     296 2658.43   382.8 2660.28     421 2662.25
   425.5 2663.02   434.1 2665.96   451.1 2675.22   453.3 2675.92   459.8 2676.33
   464.7 2677.59   472.7 2682.27   496.7 2690.36   537.2  2706.7   596.7 2724.77
#Mann= 5 ,-1,0
       0      .1       0  254.81    .045       0   277.7      .1       0
  372.85     .06       0  512.85      .1       0
Bank Sta=254.81,277.7
XS Rating Curve= 0 ,0
Exp/Cntr(USF)=0,0
Exp/Cntr=0.3,0.1

Type RM Length L Ch R = 1 ,163     ,40.9,43.3,40.5
XS GIS Cut Line= 6
2292174.60156953639607.1634919592292080.64985359 639873.15106026
2292173.48733227639923.3195027752292204.26075835639948.145123814
 2292236.0685853639994.6931632622292429.48879696 640122.13417383
#Sta/Elev= 30
       0 2733.54    53.7  2715.4   125.1 2685.47   150.9 2677.36   159.1 2673.68
   171.8  2672.9   180.3 2669.23   188.8 2667.53   197.2 2663.03   205.7 2659.99
   243.9 2658.91   256.6 2656.34   277.9  2654.5   296.8 2654.07     335 2655.75
  344.632653.681     353 2652.41   360.9 2653.68   370.7  2656.2   403.5 2656.29
   422.3 2658.37   448.4 2657.34     474 2659.21   488.5 2659.09   536.5 2663.45
   560.9  2672.3     578 2674.57   615.8 2687.58   664.6 2706.74   715.3 2723.17
#Mann= 7 ,-1,0
       0      .1       0  292.09     .06       0  344.63    .045       0
   360.9     .06       0  397.75      .1       0  466.15     .06       0
   653.7      .1       0
Bank Sta=344.63,360.9
XS Rating Curve= 0 ,0
Exp/Cntr(USF)=0,0
Exp/Cntr=0.3,0.1

Type RM Length L Ch R = 1 ,120     ,127.3,119.9,122.9
XS GIS Cut Line= 6
2292151.89866963639639.4441777512292057.94695369639905.431746052
2292150.78443237639955.6001885682292181.55785845639980.425809607
 2292213.3656854640026.9738490552292406.78589706640154.414859623
#Sta/Elev= 30
       0 2718.23    18.8  2711.9    88.9 2683.78   119.5 2673.41   129.7 2672.99
   148.5 2667.98   167.2 2660.16   201.2 2658.69   243.6 2654.41   256.3 2655.65
   292.6  2654.5   302.2  2649.9   306.6 2650.56     311  2653.3   315.4  2654.3
   328.9 2654.17   337.4 2652.25  356.782652.242   366.7 2654.49   426.8 2656.44
   448.1 2662.79   487.1 2663.82     511 2662.32   558.9 2669.29   568.5 2673.01
     602 2680.51   635.6 2691.14   678.7 2708.42   688.3 2713.39   715.3 2722.82
#Mann= 5 ,-1,0
       0      .1       0     230     .06       0   337.4    .045       0
  356.78     .06       0   673.7      .1       0
Bank Sta=337.4,356.78
XS Rating Curve= 0 ,0
Exp/Cntr(USF)=0,0
Exp/Cntr=0.3,0.1

Type RM Length L Ch R = 1 ,0       ,506.9,501.5,496.9
XS GIS Cut Line= 4
2291640.08272648639974.7499509422291941.32283109639972.744093601
2292138.83302607640052.7463024162292436.38430207640213.389838288
#Sta/Elev= 30
       0 2746.76    60.1 2729.72    72.1 2724.78    92.1 2722.68   172.1 2695.62
     216 2682.99   220.1 2681.39   232.1 2672.53   264.3 2671.99   288.4 2659.94
   309.9 2651.14   343.7 2650.23  367.382647.995   377.5 2646.75  389.042648.029
   398.3  2649.9   425.2 2647.77   442.4 2652.78   507.2    2654   530.4 2660.25
   592.4 2662.16   629.5 2665.98   647.7 2666.64   654.4 2669.62   688.6 2678.69
   751.8 2700.13     775 2709.71   806.8 2725.45   815.9 2727.32   852.5 2740.66
#Mann= 9 ,-1,0
       0      .1       0     150     .06       0  311.25      .1       0
  367.38    .045       0  389.04      .1       0  451.25     .06       0
  564.34      .1       0  674.34     .06       0  784.34      .1       0
Bank Sta=367.38,389.04
XS Rating Curve= 0 ,0
Exp/Cntr=0.3,0.1
LCMann Table=0

Chan Stop Cuts=-1
Use User Specified Reach Order=0
Composite Channel Slope=5